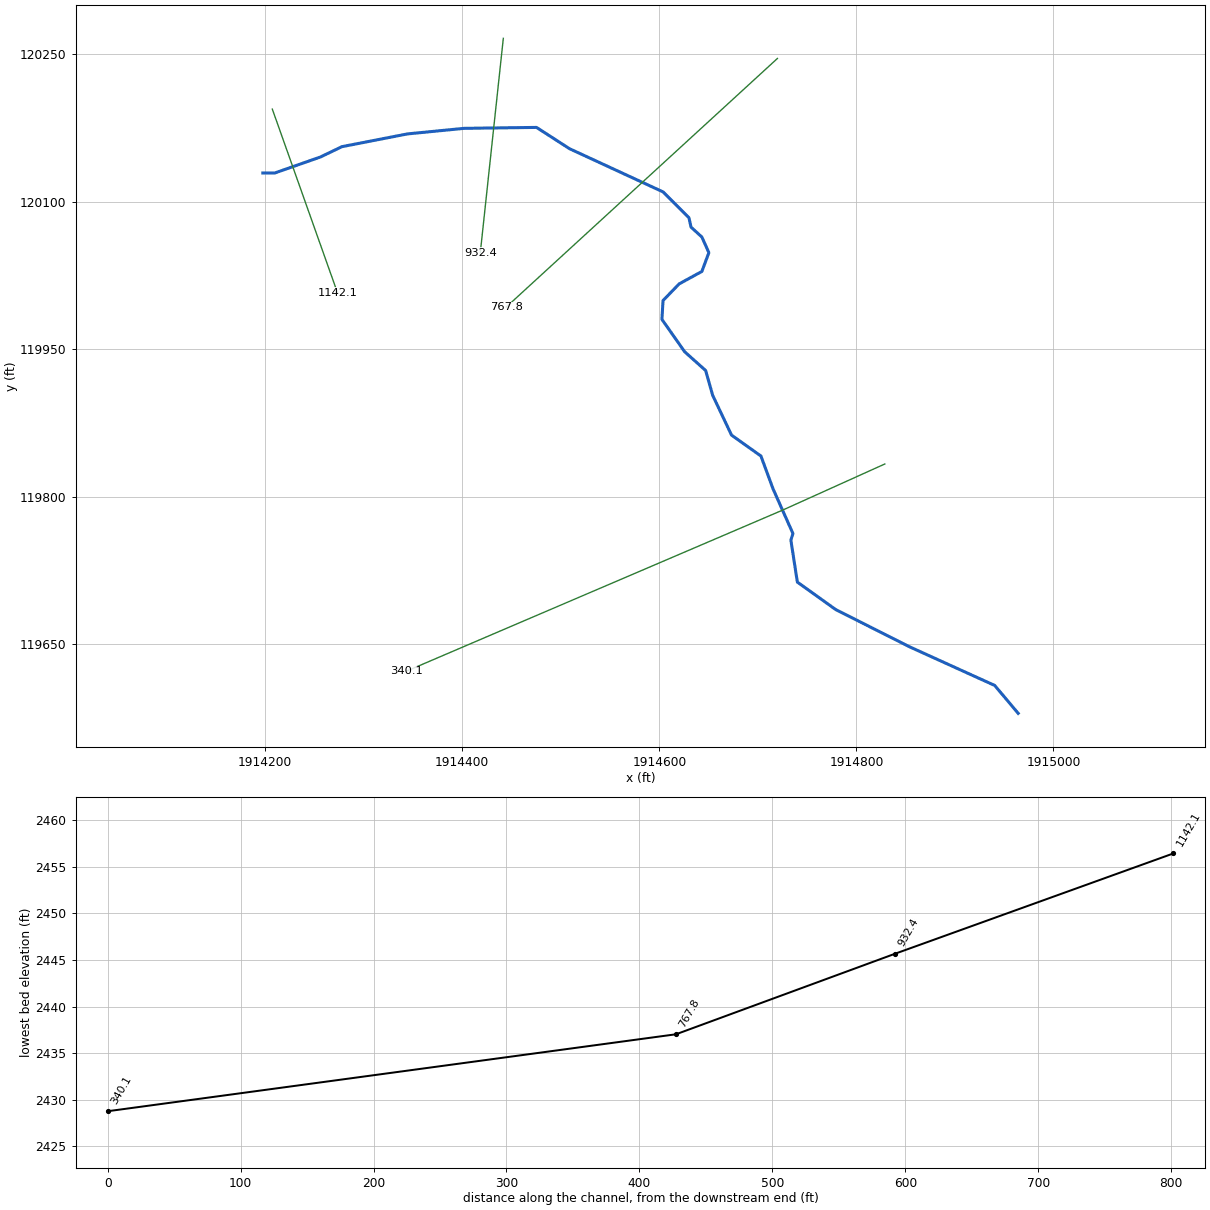
--- NthFrkTrb.prj (project) ---

Proj Title=NthFrkTrb
Current Plan=p01
Default Exp/Contr=0,0
English Units
Geom File=g01
Flow File=f01
Plan File=p01
BEGIN DESCRIPTION:
END DESCRIPTION:
DSS Export Rating Curves= 0
DSS Export Rating Curve Sorted= 0
DSS Export Volume Flow Curves= 0
DXF OffsetX= 0
DXF OffsetY= 0
DXF ScaleX= 0
DXF ScaleY= 0

--- NthFrkTrb.p01 (plan) ---

Plan Title=Floodplain
Program Version=4.00
Geom File=g01
Flow File=f01
K Sum by GR=0
Std Step Tol=0.01
Critical Tol=0.01
Num of Std Step Trials=20
Max Error Tol=0.3
Flow Tol Ratio=0.001
Split Flow NTrial=30
Split Flow Tol=0.02
Split Flow Ratio=0.02
Log Output Level=0
Friction Slope Method=1
Unsteady Friction Slope Method=2
Unsteady Bridges Friction Slope Method=1
Global Log Level=0
CheckData=False
Run HTab=0
Run UNet=0
Run PostProcess=0
UNET Theta=0
UNET Theta Warmup=0
UNET ZTol=0
UNET ZSATol=0
UNET MxIter=0
UNET MaxInSteps=0
UNET DtIC=0
UNET DtMin=0
UNET MaxCRTS=0
UNET WFStab=0
UNET SFStab=0
UNET WFX=0
UNET SFX=0
UNET DSS MLevel=0
UNET DZMax Abort=0
UNET Convert EG Bridges=0
UNET Use Existing IB Tables=0
UNET Froude Limit=0
UNET Froude Power=0
Write IC File=0
Echo Input=False
Echo Output=False
Write Detailed=0

--- NthFrkTrb.f01 (steady flow) ---

Flow Title=NFF Regression Equation
Program Version=4.00
Number of Profiles=1
Profile Names=P100yr
River Rch & RM=NthFrkTrb,Main      ,1142.1
539.7373
River Rch & RM=NthFrkTrb,Main      ,340.1
547.9075
Boundary for River Rch & Prof#=NthFrkTrb,Main      ,1
Up Type=0
Dn Type=3
Dn Slope=0.041937

--- NthFrkTrb.g01 (geometry) ---

Geom Title=USGS 3m DEM
Program Version=4.10

River Reach=NthFrkTrb       ,Main
Reach XY= 30
       1914197.7      120129.466     1914209.857      120129.466
     1914256.052      120145.675     1914277.935       120156.21
     1914344.391      120169.178     1914401.933      120174.851
     1914475.404      120175.799     1914508.855      120154.154
      1914603.83      120110.219     1914630.078      120083.961
     1914632.209      120074.375     1914643.192      120064.333
     1914650.309      120048.458     1914643.192      120029.298
       1914620.2      120016.707     1914603.777      119999.737
     1914602.683      119980.577     1914625.674      119947.731
     1914647.024      119928.572     1914654.141       119903.39
       1914673.3       119862.88     1914703.124      119841.639
     1914715.423      119808.238     1914735.624      119762.777
     1914733.517      119756.132     1914740.086      119713.433
     1914778.954      119685.515     1914853.907      119647.644
      1914940.38      119608.309     1914964.227       119579.92

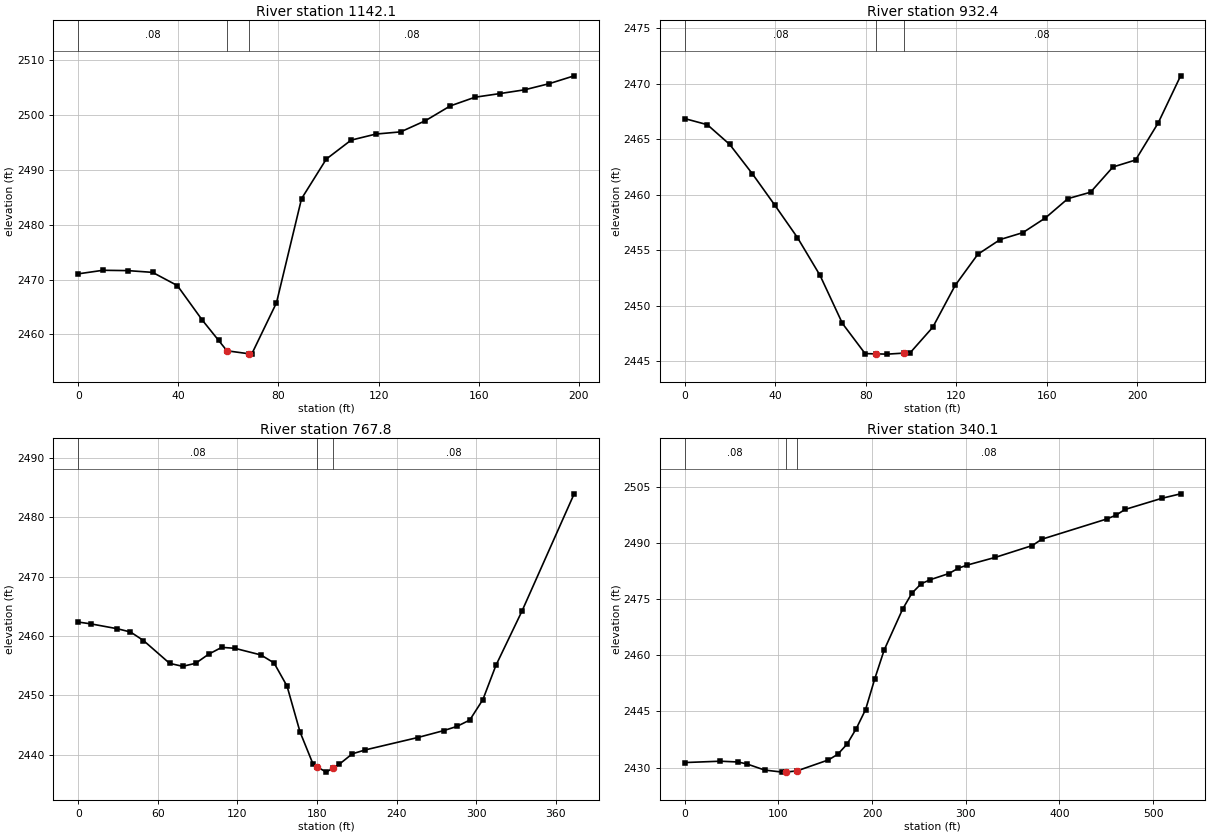
Type RM Length L Ch R = 1 ,1142.1  ,218.9,209.5,200
XS GIS Cut Line= 2
      1914207.29        120194.4     1914273.434      120007.641
#Sta/Elev= 23
       0 2471.06     9.9 2471.71    19.8 2471.65    29.7 2471.33    39.6 2468.92
    49.5 2462.66    56.1 2458.91    59.4 2457.03    68.1 2456.49    69.3 2456.42
    79.2 2465.79    89.2 2484.76    99.1 2491.99     109 2495.44   118.9 2496.55
   128.8 2496.95   138.7 2498.99   148.6 2501.68   158.5 2503.27   168.4 2503.93
   178.3 2504.62   188.2 2505.75   198.1 2507.17
#Mann= 3 , 0 , 0
       0     .08       0    59.4    .045       0    68.1     .08       0
Bank Sta=59.4,68.1
XS Rating Curve= 0 ,0
Exp/Cntr=0.3,0.1

Type RM Length L Ch R = 1 ,932.4   ,180.5,164.7,148.8
XS GIS Cut Line= 2
     1914441.712       120266.38     1914418.367      120048.495
#Sta/Elev= 25
       0 2466.87      10 2466.32    19.9 2464.54    29.9  2461.9    39.8 2459.08
    49.8 2456.16    59.8 2452.75    69.7 2448.42    79.7 2445.71    84.7 2445.68
    89.6 2445.66    96.7 2445.75    99.6 2445.78   109.6 2448.08   119.5 2451.85
   129.5 2454.65   139.4 2455.98   149.4  2456.6   159.4 2457.93   169.3 2459.66
   179.3 2460.24   189.2 2462.51   199.2 2463.14   209.2 2466.48   219.1 2470.72
#Mann= 3 , 0 , 0
       0     .08       0    84.7    .045       0    96.7     .08       0
Bank Sta=84.7,96.7
XS Rating Curve= 0 ,0
Exp/Cntr=0.3,0.1

Type RM Length L Ch R = 1 ,767.8   ,434.5,427.5,420.1
XS GIS Cut Line= 2
     1914719.904      120245.953      1914444.63      119993.051
#Sta/Elev= 30
       0 2462.35     9.8 2462.03    29.5 2461.22    39.4 2460.67    49.2 2459.23
    68.9 2455.38    78.7 2454.88    88.5 2455.39    98.4 2456.94   108.2 2458.08
     118 2457.92   137.7  2456.8   147.6 2455.45   157.4 2451.54   167.2  2443.8
   177.1 2438.32   180.2 2437.91   186.9 2437.03   192.2 2437.74   196.7 2438.35
   206.6 2440.12   216.4 2440.78   255.8 2442.86   275.4 2444.03   285.3 2444.73
   295.1 2445.81     305 2449.26   314.8 2455.02   334.5 2464.21   373.8 2483.98
#Mann= 3 , 0 , 0
       0     .08       0   180.2    .045       0   192.2     .08       0
Bank Sta=180.2,192.2
XS Rating Curve= 0 ,0
Exp/Cntr=0.3,0.1

Type RM Length L Ch R = 1 ,340.1   ,334,340.1,346.6
XS GIS Cut Line= 3
     1914828.847      119833.527     1914725.052      119786.569
      1914343.19      119622.754
#Sta/Elev= 30
       0 2431.34      38  2431.7      57 2431.49    66.5 2430.96    85.4 2429.33
   104.4 2428.78   107.9  2428.8   119.9 2429.11   153.5 2432.05   163.4 2433.55
   173.3 2436.26   183.2 2440.43   193.1  2445.5     203 2453.81   212.9  2461.4
   232.6 2472.34   242.5 2476.61   252.4 2479.14   262.3 2480.25   282.1 2481.89
     292  2483.3   301.9 2484.17   331.6 2486.21   371.2 2489.38     381 2491.04
   450.3 2496.45   460.2 2497.46   470.1 2499.02   509.6 2502.02   529.4  2503.2
#Mann= 3 , 0 , 0
       0     .08       0   107.9    .045       0   119.9     .08       0
Bank Sta=107.9,119.9
XS Rating Curve= 0 ,0
Exp/Cntr=0.3,0.1

Chan Stop Cuts=-1
Use User Specified Reach Order=0
Composite Channel Slope=5